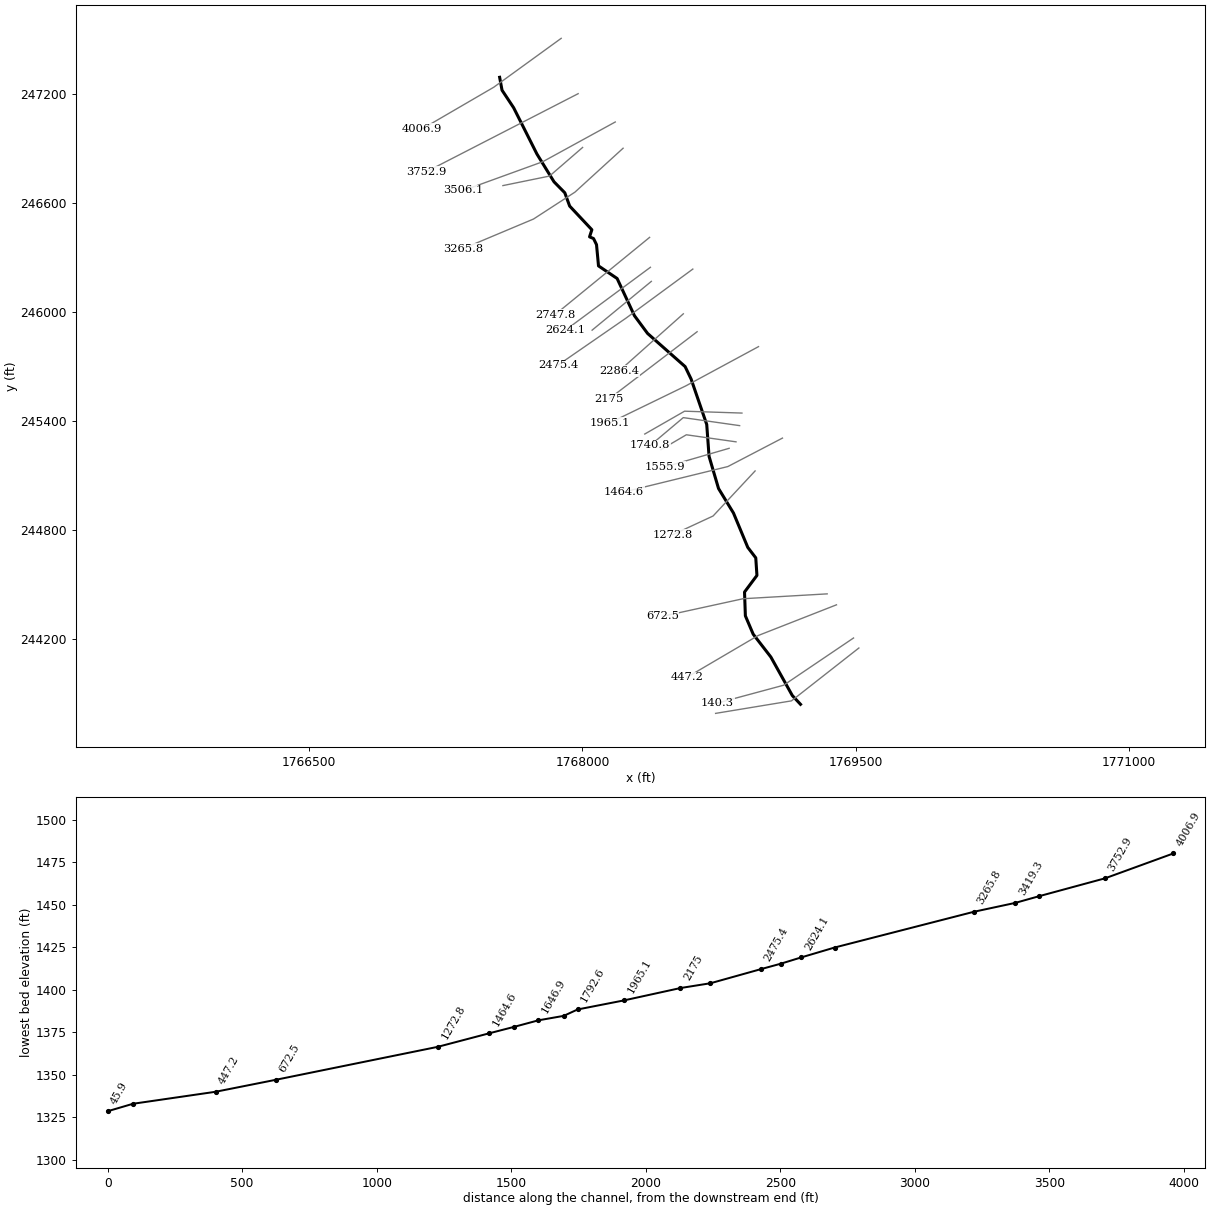
--- ReedyBr2.prj (project) ---

Proj Title=ReedyBr2
Current Plan=p01
Default Exp/Contr=0,0
English Units
Geom File=g01
Flow File=f01
Plan File=p01
BEGIN DESCRIPTION:
END DESCRIPTION:
DSS Export Rating Curves= 0
DSS Export Rating Curve Sorted= 0
DSS Export Volume Flow Curves= 0
DXF OffsetX= 0
DXF OffsetY= 0
DXF ScaleX= 0
DXF ScaleY= 0

--- ReedyBr2.p01 (plan) ---

Plan Title=Floodplain
Program Version=4.00
Geom File=g01
Flow File=f01
K Sum by GR=0
Std Step Tol=0.01
Critical Tol=0.01
Num of Std Step Trials=20
Max Error Tol=0.3
Flow Tol Ratio=0.001
Split Flow NTrial=30
Split Flow Tol=0.02
Split Flow Ratio=0.02
Log Output Level=0
Friction Slope Method=1
Unsteady Friction Slope Method=2
Unsteady Bridges Friction Slope Method=1
Global Log Level=0
CheckData=False
Run HTab=0
Run UNet=0
Run PostProcess=0
UNET Theta=0
UNET Theta Warmup=0
UNET ZTol=0
UNET ZSATol=0
UNET MxIter=0
UNET MaxInSteps=0
UNET DtIC=0
UNET DtMin=0
UNET MaxCRTS=0
UNET WFStab=0
UNET SFStab=0
UNET WFX=0
UNET SFX=0
UNET DSS MLevel=0
UNET DZMax Abort=0
UNET Convert EG Bridges=0
UNET Use Existing IB Tables=0
UNET Froude Limit=0
UNET Froude Power=0
Write IC File=0
Echo Input=False
Echo Output=False
Write Detailed=0

--- ReedyBr2.f01 (steady flow) ---

Flow Title=NFF Regression Equation
Program Version=4.00
Number of Profiles=1
Profile Names=P100yr
River Rch & RM=ReedyBr2,Main      ,4006.9
557.3963
River Rch & RM=ReedyBr2,Main      ,3265.8
607.4828
River Rch & RM=ReedyBr2,Main      ,1464.6
659.6553
River Rch & RM=ReedyBr2,Main      ,672.5
725.8273
River Rch & RM=ReedyBr2,Main      ,140.3
744.4125
Boundary for River Rch & Prof#=ReedyBr2,Main      ,1
Up Type=0
Dn Type=3
Dn Slope=0.034176

--- ReedyBr2.g01 (geometry) ---

Geom Title=USGS 10m DEM
Program Version=4.00

River Reach=ReedyBr2        ,Main
Reach XY= 30
     1767545.244      247289.921     1767558.321      247218.936
     1767622.073      247122.418      1767749.65      246868.282
     1767843.666       246715.07     1767902.861      246654.714
     1767929.557      246581.591     1768051.426      246451.412
     1768038.651      246412.175     1768060.551       246403.05
     1768076.976      246369.288     1768087.926      246252.488
     1768190.126      246183.138     1768285.026      245978.739
     1768357.113      245881.102     1768563.337      245698.602
     1768596.187      245630.165     1768681.962      245380.141
     1768694.737      245204.941     1768746.749      245027.917
     1768828.874      244892.867     1768907.349       244703.98
     1768951.148      244646.493     1768957.536      244549.768
     1768889.449      244458.422     1768894.092      244327.527
     1768937.038      244226.546     1769033.885      244101.121
     1769151.744      243889.137     1769196.779      243840.824

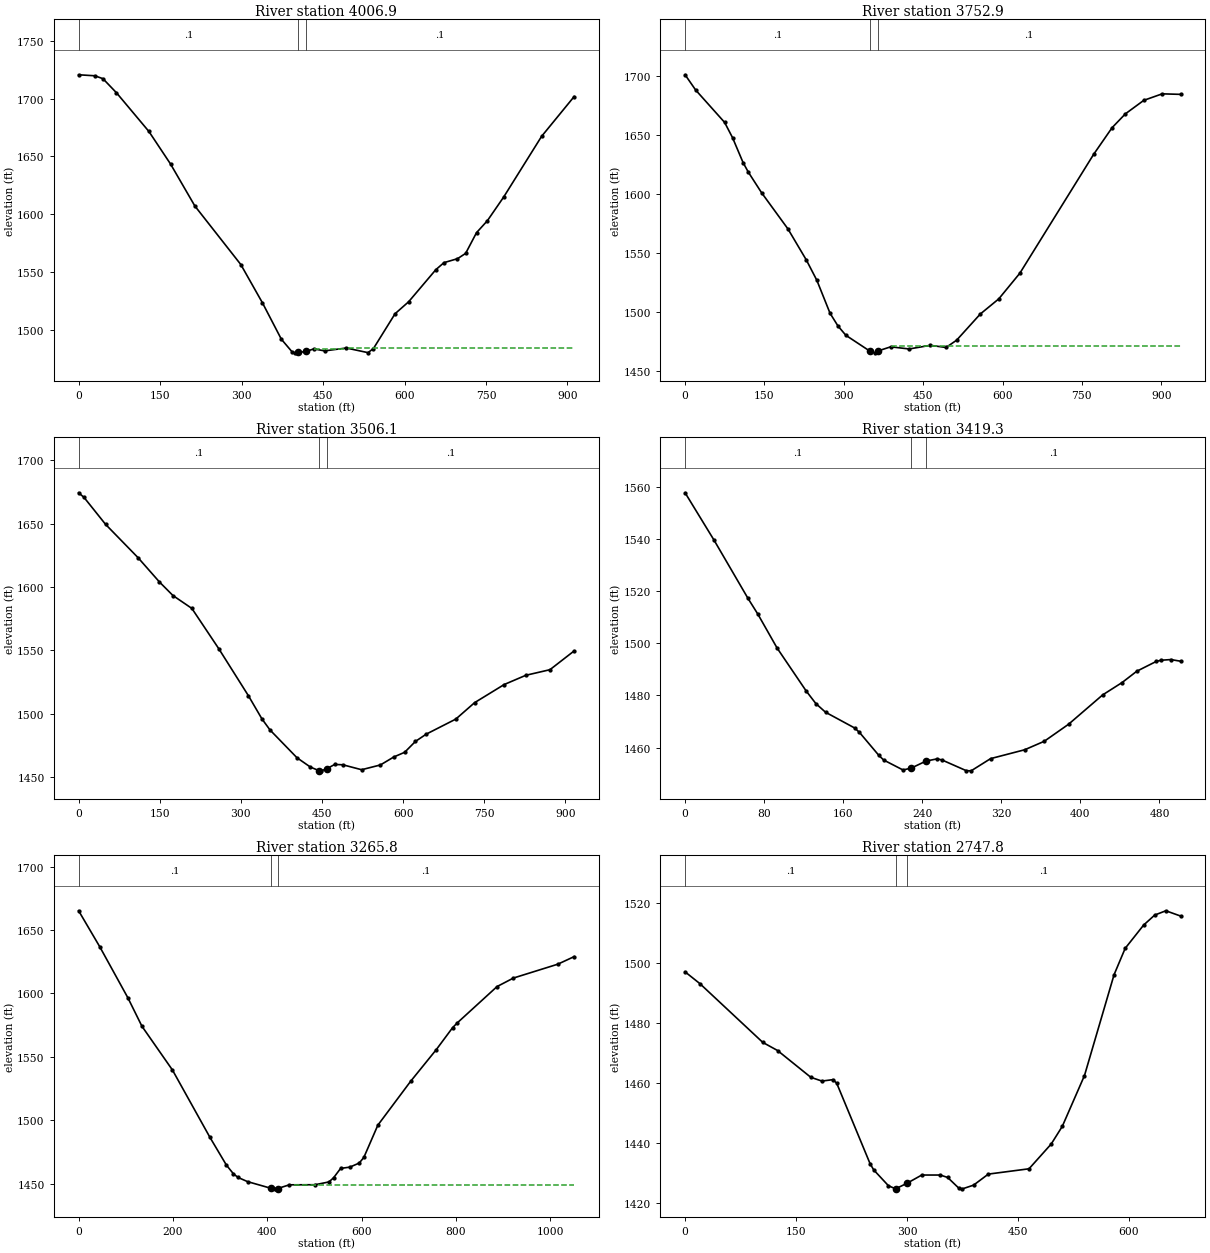
Type RM Length L Ch R = 1 ,4006.9  ,258,254,250.1
XS GIS Cut Line= 3
     1767883.112      247504.281     1767512.738      247235.229
     1767120.142      247006.216
#Sta/Elev= 30
       0 1720.57    29.9  1719.7    44.8 1717.18    69.7    1705   129.4 1671.55
   169.2 1643.43     214 1607.12   298.6 1556.51   338.4 1523.43   373.2 1491.99
   393.1 1480.98   398.1  1480.2   403.9  1480.5   418.9 1481.37   432.9 1483.62
   452.8 1481.88   492.8 1484.37   532.7 1480.37   542.7 1483.88   582.6 1514.02
   607.6 1524.38   657.6 1552.08   672.6 1558.17   697.5 1561.58   712.5 1566.18
   732.5 1584.07   752.5 1594.41   782.4  1614.8   852.4 1667.39   912.3 1701.76
#Mann= 3 , 0 , 0
       0      .1       0   403.9    .045       0   418.9      .1       0
#XS Ineff= 2 ,-1
  432.87  490.62 1483.69  495.72   912.3 1484.38
Permanent Ineff=
       F       F
Bank Sta=403.9,418.9
XS Rating Curve= 0 ,0
Exp/Cntr=0.3,0.1

Type RM Length L Ch R = 1 ,3752.9  ,246.1,246.9,244.3
XS GIS Cut Line= 2
     1767976.217      247199.867     1767143.549      246770.762
#Sta/Elev= 30
       0 1700.67    19.9 1687.82    74.7  1660.4    89.7 1647.47   109.6 1626.42
   119.6 1618.28   144.5 1600.98   194.3  1570.4   229.2 1544.04   249.1 1526.84
     274 1499.01     289 1488.23   303.9 1480.38   349.1 1467.04   358.8 1465.55
   364.1 1467.07   388.6 1470.64   423.5 1468.83   463.4 1471.89   493.3  1470.1
   513.2 1476.22     558 1498.37   592.9 1511.17   632.8  1532.9   772.3 1633.43
   807.2 1655.97   832.1 1667.58     867 1679.04   901.8 1684.55   936.7 1684.11
#Mann= 3 , 0 , 0
       0      .1       0   349.1    .045       0   364.1      .1       0
#XS Ineff= 2 , 0
                          390.61         1470.98
Permanent Ineff=
       F       F
Bank Sta=349.1,364.1
XS Rating Curve= 0 ,0
Exp/Cntr=0.3,0.1

Type RM Length L Ch R = 1 ,3506.1  ,81.9,86.7,84.9
XS GIS Cut Line= 3
     1768179.861       247044.12     1767782.254      246825.764
     1767347.268      246667.677
#Sta/Elev= 30
       0 1674.46      10 1670.79    49.8 1649.54   109.7 1623.31   149.5 1604.02
   174.5 1593.31   209.4 1583.17   259.2 1551.34     314 1514.22     339 1495.94
   353.9 1487.22   403.8 1465.27   428.7 1457.89   444.6 1455.08   448.6 1454.94
   459.6 1456.75   473.5 1459.98   488.5 1459.73   523.3 1455.82   558.1 1459.59
     583 1465.92   602.9 1469.58   622.8 1478.15   642.7 1483.88   697.5 1495.79
   732.3 1508.78     787 1523.08   826.9 1530.36   871.6 1534.79   916.4 1549.63
#Mann= 3 , 0 , 0
       0      .1       0   444.6    .045       0   459.6      .1       0
#XS Ineff= 2 , 0
                          483.61         1459.56
Permanent Ineff=
       F       F
Bank Sta=444.6,459.6
XS Rating Curve= 0 ,0
Exp/Cntr=0.3,0.1

Type RM Length L Ch R = 1 ,3419.3  ,156.7,153.5,160.2
XS GIS Cut Line= 3
     1768000.526      246903.987     1767819.089      246746.672
      1767563.19      246694.234
#Sta/Elev= 30
       0 1557.68    29.4 1539.45    63.7 1517.15    73.5 1511.23    93.1 1498.15
   122.5  1481.7   132.3 1476.87   142.1 1473.55   171.5 1467.52   176.4 1465.83
     196 1457.02   200.9 1455.23   220.5 1451.41   228.8 1452.13   243.8 1454.83
   254.9 1455.66   259.8 1455.27   284.5 1451.14   289.4 1451.08   309.1 1455.76
   343.6 1459.16   363.4 1462.41     388 1468.94   422.5 1480.19   442.2 1484.94
     457 1489.26   476.7 1493.02   481.6 1493.48   491.5 1493.74   501.4  1493.1
#Mann= 3 , 0 , 0
       0      .1       0   228.8    .045       0   243.8      .1       0
#XS Ineff= 2 , 0
                          254.56         1455.51
Permanent Ineff=
       F       F
Bank Sta=228.8,243.8
XS Rating Curve= 0 ,0
Exp/Cntr=0.3,0.1

Type RM Length L Ch R = 1 ,3265.8  ,501.6,518,520.4
XS GIS Cut Line= 4
     1768222.864      246899.792     1767958.523      246658.172
     1767731.014      246510.234     1767342.776      246346.766
#Sta/Elev= 30
       0 1665.24    44.8 1636.86   104.4  1596.6   134.3  1574.1     199 1539.57
   278.6 1486.37   313.4 1464.57   328.3 1457.69   338.2 1454.82   358.1 1451.56
     407 1446.38   417.3 1445.86     422 1446.11   446.9 1449.03   501.2  1449.1
   530.8  1451.3   540.7 1454.63   555.5 1461.96   575.2    1463     595 1466.21
   604.8 1470.64   634.5  1496.1   703.8  1530.6   758.4 1555.69     793 1573.02
     803 1576.82   887.2 1605.43   921.9 1612.16  1016.1  1623.1  1050.8 1629.08
#Mann= 3 , 0 , 0
       0      .1       0     407    .045       0     422      .1       0
#XS Ineff= 2 , 0
                           456.7         1449.09
Permanent Ineff=
       F       F
Bank Sta=407,422
XS Rating Curve= 0 ,0
Exp/Cntr=0.3,0.1

Type RM Length L Ch R = 1 ,2747.8  ,124.6,123.7,123
XS GIS Cut Line= 2
     1768368.389      246409.417     1767850.011       245984.98
#Sta/Elev= 30
       0 1497.08      20 1493.16     105 1473.59     125 1470.88     170 1461.95
     185  1460.7     200 1461.18     205 1459.98     250 1433.24     255 1431.11
     275 1425.82   284.6 1424.81   299.6  1426.6     320  1429.4     345  1429.4
     355 1428.59     370 1425.05     375  1424.8     390 1426.03     410 1429.71
     465 1431.48     495 1439.73     510 1445.62     540 1462.55     580 1496.14
     595 1504.91     620 1512.68     635 1516.01     650 1517.43     670 1515.67
#Mann= 3 , 0 , 0
       0      .1       0   284.6    .045       0   299.6      .1       0
#XS Ineff= 2 , 0
                          332.95         1429.37
Permanent Ineff=
       F       F
Bank Sta=284.6,299.6
XS Rating Curve= 0 ,0
Exp/Cntr=0.3,0.1

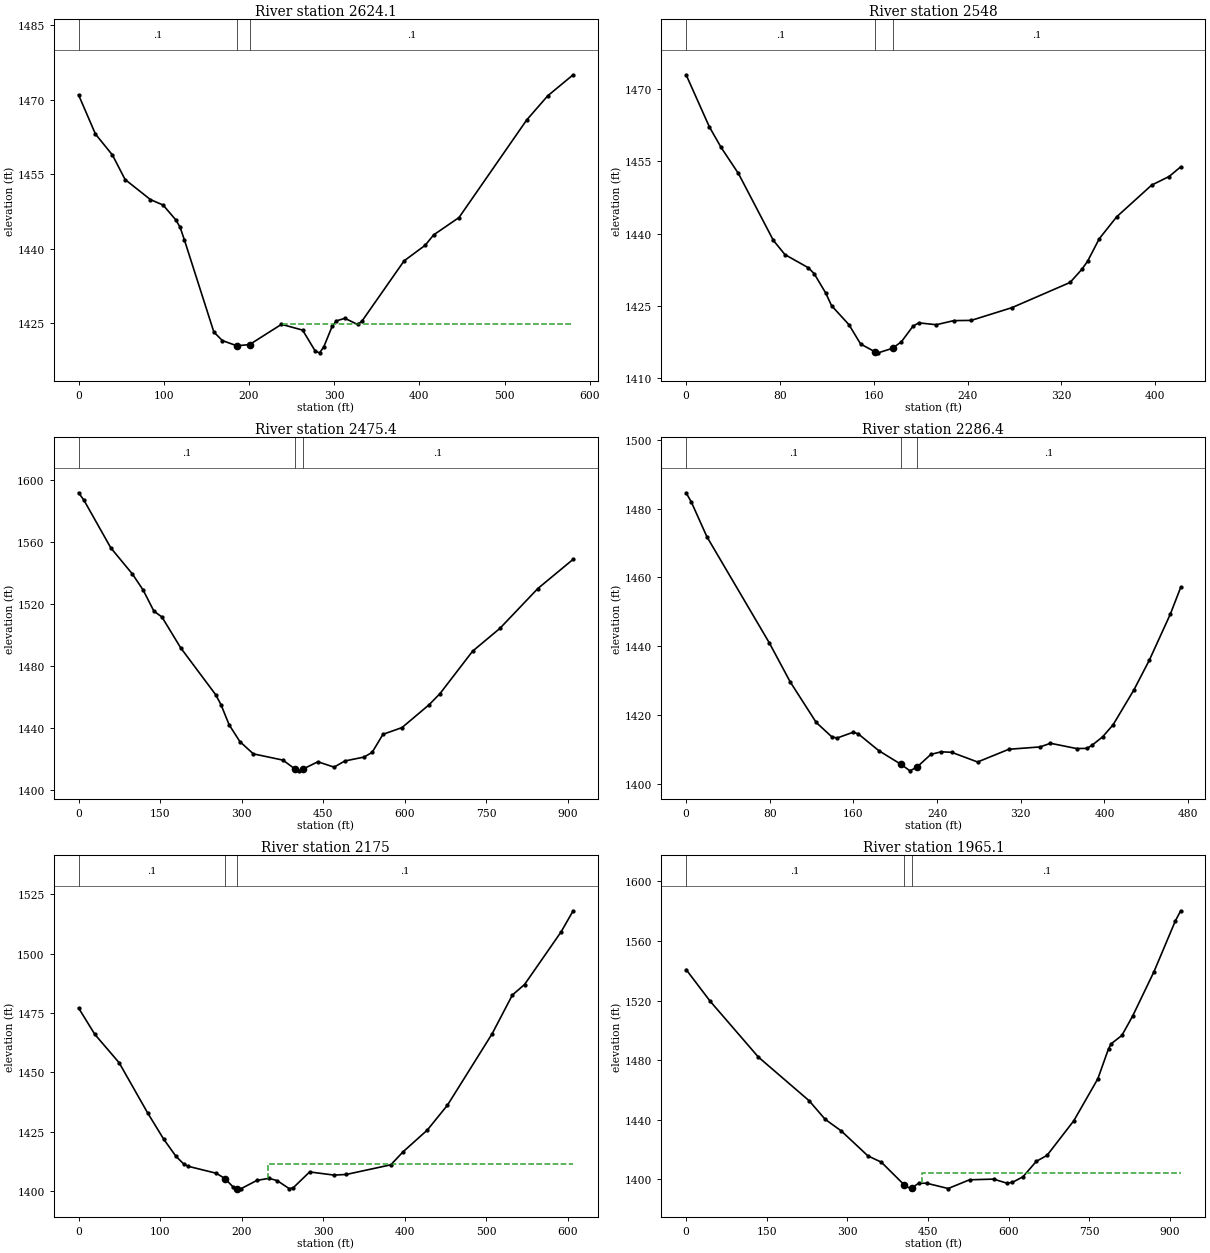
Type RM Length L Ch R = 1 ,2624.1  ,74.9,76.1,77.2
XS GIS Cut Line= 2
     1768372.802      246244.841     1767906.467      245898.962
#Sta/Elev= 30
       0 1470.98    19.8 1463.09    39.7 1458.88    54.6 1453.93    84.4 1449.88
    99.2 1448.79   114.1  1445.8   119.1 1444.34   124.1 1441.82   158.8  1423.2
   168.7 1421.48   185.8 1420.42   200.8 1420.67   238.2 1424.75     263 1423.58
   277.9 1419.33   282.9    1419   287.8 1420.18   297.8 1424.39   302.7 1425.44
   312.6 1425.96   327.5 1424.72   332.5 1425.35   382.1 1437.53   406.9 1440.68
   416.8 1442.77   446.6 1446.27     526 1465.92   550.8 1470.81   580.6 1475.04
#Mann= 3 , 0 , 0
       0      .1       0   185.8    .045       0   200.8      .1       0
#XS Ineff= 2 , 0
                          240.21         1424.78
Permanent Ineff=
       F       F
Bank Sta=185.8,200.8
XS Rating Curve= 0 ,0
Exp/Cntr=0.3,0.1

Type RM Length L Ch R = 1 ,2548    ,73.8,72.7,71.5
XS GIS Cut Line= 2
     1768377.964      246167.405     1768052.735      245898.962
#Sta/Elev= 30
       0 1472.96    19.8 1462.17    29.8  1457.9    44.6 1452.49    74.4 1438.61
    84.3 1435.66   104.2 1432.94   109.2 1431.71   119.1 1427.67     124 1425.08
   138.9 1421.11   148.8 1417.12     161 1415.51   163.7 1415.29     176 1416.23
   183.6  1417.6   193.5 1420.83   198.4 1421.51   213.3 1421.12   228.2 1421.97
   243.1 1422.02   277.8 1424.66   327.4 1429.89   337.4  1432.6   342.3 1434.28
   352.2 1438.93   367.1  1443.5   396.9 1450.07   411.8 1451.86   421.7 1453.86
#Mann= 3 , 0 , 0
       0      .1       0     161    .045       0     176      .1       0
Bank Sta=161,176
XS Rating Curve= 0 ,0
Exp/Cntr=0.3,0.1

Type RM Length L Ch R = 1 ,2475.4  ,187,189,191
XS GIS Cut Line= 3
     1768605.719      246235.066     1768239.048      245965.278
     1767864.984      245706.309
#Sta/Elev= 30
       0 1591.51     9.9 1586.69    59.4 1555.92      99 1539.13   118.8 1528.78
   138.6 1515.16   153.4 1511.38     188 1491.44   252.4 1461.22   262.2 1454.73
   277.1 1441.82   296.9 1430.98   321.6 1423.09   376.1 1419.06   398.3 1413.32
   405.8 1412.14   413.3 1413.34   440.4 1417.99   470.2 1414.53   490.2 1418.52
   525.2 1421.01   540.2 1424.03   560.2  1435.7   595.2 1440.04   645.2 1454.81
   665.2 1461.99   725.2 1489.36   775.2 1503.98   845.2 1529.74   910.2  1548.6
#Mann= 3 , 0 , 0
       0      .1       0   398.3    .045       0   413.3      .1       0
#XS Ineff= 2 , 0
                          440.21         1417.68
Permanent Ineff=
       F       F
Bank Sta=398.3,413.3
XS Rating Curve= 0 ,0
Exp/Cntr=0.3,0.1

Type RM Length L Ch R = 1 ,2286.4  ,113.2,111.4,109.6
XS GIS Cut Line= 2
       1768553.5      245988.889     1768200.738      245673.984
#Sta/Elev= 30
       0 1484.57       5 1481.88    19.9 1471.78    79.6 1440.93    99.6 1429.58
   124.4 1417.83   139.4 1413.63   144.4 1413.31   159.3 1414.94   164.3 1414.59
   184.2 1409.64   205.6 1405.64     214 1403.77   220.6 1404.82     234 1408.55
   243.9  1409.3   253.9 1409.16   278.7 1406.34   308.6 1410.04   338.5 1410.72
   348.4 1411.78   373.3 1410.25   383.3  1410.3   388.2 1411.22   398.2 1413.64
   408.2 1417.12   428.1 1427.25     443 1435.98   462.9 1449.24   472.9 1457.07
#Mann= 3 , 0 , 0
       0      .1       0   205.6    .045       0   220.6      .1       0
#XS Ineff= 2 , 0
                          248.01         1409.23
Permanent Ineff=
       F       F
Bank Sta=205.6,220.6
XS Rating Curve= 0 ,0
Exp/Cntr=0.3,0.1

Type RM Length L Ch R = 1 ,2175    ,213.4,209.9,206.4
XS GIS Cut Line= 2
       1768629.2      245890.358     1768147.378      245522.108
#Sta/Elev= 30
       0 1477.12    19.9 1466.03    49.7 1454.08    84.5 1433.03   104.4 1421.85
   119.3  1414.7   129.2 1411.31   134.2 1410.46     169  1407.5   179.6 1405.23
   188.9 1401.93   194.6 1401.07   198.8 1400.95   218.7 1404.51   233.6 1405.38
   243.6  1404.4   258.5 1400.98   263.4 1401.48   283.3 1408.07   313.2 1406.74
   328.1    1407   382.8 1411.07   397.7  1416.5   427.5 1425.69   452.3  1436.2
     507 1466.24   531.9 1482.61   546.8 1487.02   591.5 1509.14   606.4 1518.08
#Mann= 3 , 0 , 0
       0      .1       0   179.6    .045       0   194.6      .1       0
#XS Ineff= 2 , 0
                          231.89         1411.24
Permanent Ineff=
       F       F
Bank Sta=179.6,194.6
XS Rating Curve= 0 ,0
Exp/Cntr=0.3,0.1

Type RM Length L Ch R = 1 ,1965.1  ,185.1,172.5,160
XS GIS Cut Line= 3
     1768966.205      245808.412     1768567.983      245592.905
     1768147.661      245388.264
#Sta/Elev= 30
       0 1540.81    44.8 1519.53   134.4 1482.11   228.9 1452.79   258.7 1440.33
   288.6 1432.55   338.4 1415.75   363.2 1411.59     406 1396.26     418 1393.67
     421 1394.53   432.9 1397.47   447.8 1397.41   487.6 1393.89   527.4 1399.74
   572.2 1400.19     597 1397.46     607    1398   626.9 1401.78   651.7 1412.13
   671.6 1416.12   721.4 1439.35   766.1  1467.5     786 1487.65     791    1491
   810.9 1496.62   830.8 1509.53   870.6 1539.37   910.3 1573.38   920.3 1580.24
#Mann= 3 , 0 , 0
       0      .1       0     406    .045       0     421      .1       0
#XS Ineff= 2 , 0
                          439.33         1404.42
Permanent Ineff=
       F       F
Bank Sta=406,421
XS Rating Curve= 0 ,0
Exp/Cntr=0.3,0.1

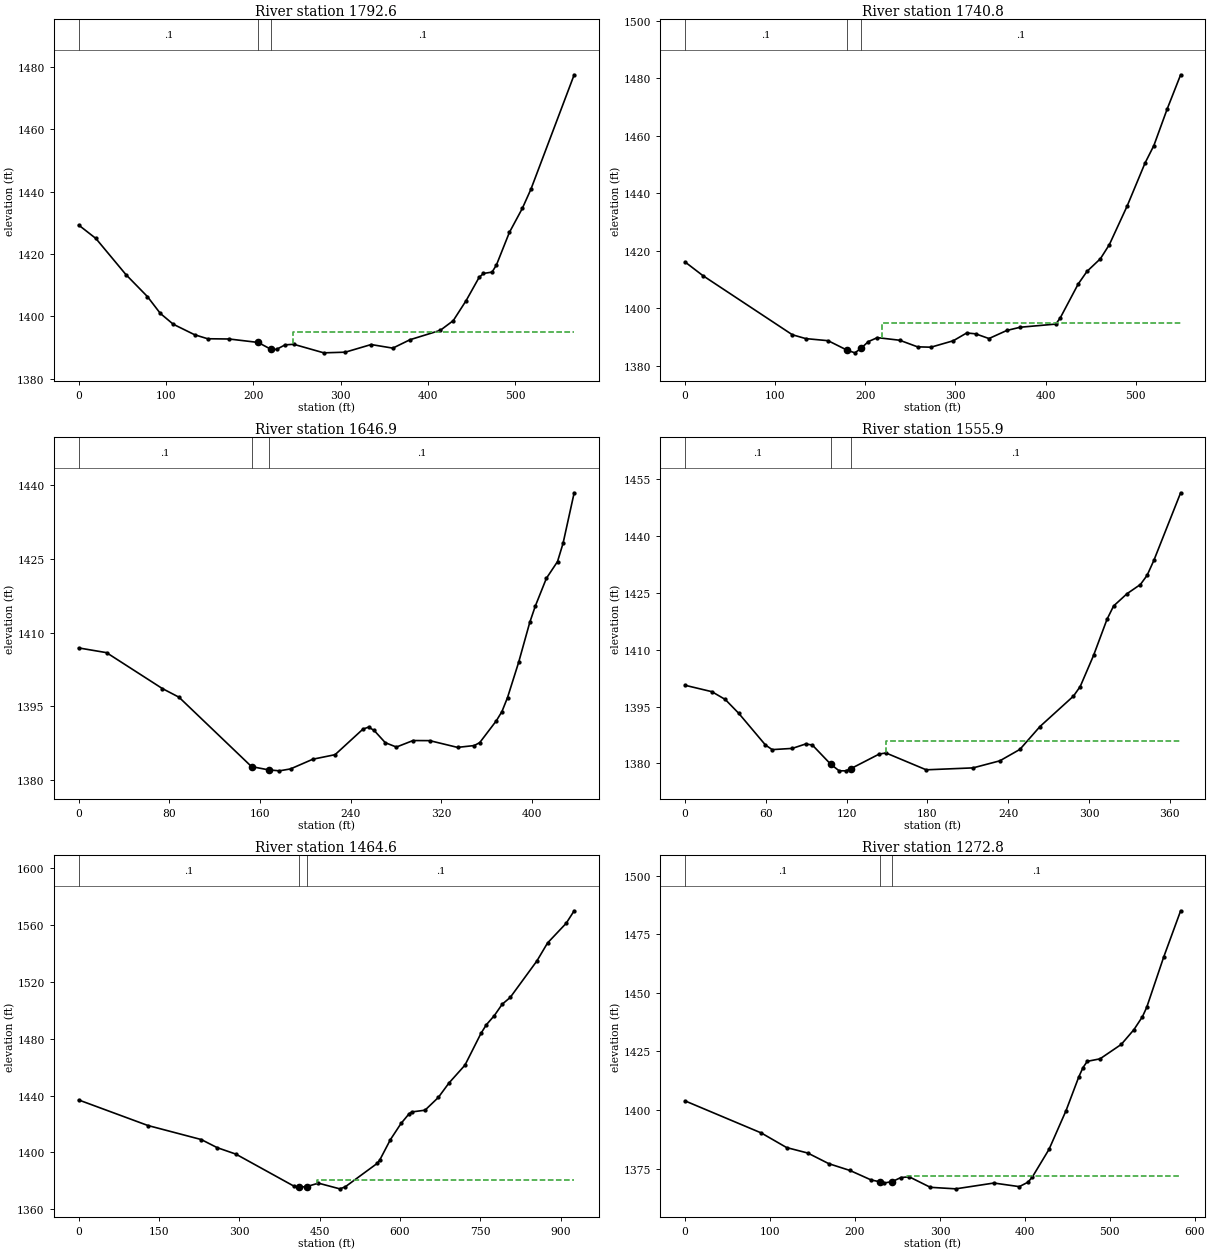
Type RM Length L Ch R = 1 ,1792.6  ,54,51.7,49.4
XS GIS Cut Line= 3
     1768875.273      245442.952     1768560.368      245453.276
     1768341.828      245327.658
#Sta/Elev= 30
       0 1429.34    19.7 1425.03    54.2 1413.41    78.8 1406.36    93.5 1400.98
   108.3 1397.51   132.9 1394.12   147.7 1392.85   172.3 1392.77   205.4 1391.67
   220.4 1389.43   226.5 1389.44   236.3 1390.89   246.2 1391.07   280.6 1388.33
   305.2 1388.54   334.8 1390.99   359.6 1389.84   379.3 1392.54   413.9 1395.54
   428.8 1398.66   443.6 1405.12   458.4 1412.54   463.4  1413.8   473.2 1414.23
   478.2  1416.5     493 1426.94   507.8 1434.65   517.7 1440.83   567.2 1477.54
#Mann= 3 , 0 , 0
       0      .1       0   205.4    .045       0   220.4      .1       0
#XS Ineff= 2 , 0
                             245         1395.17
Permanent Ineff=
       F       F
Bank Sta=205.4,220.4
XS Rating Curve= 0 ,0
Exp/Cntr=0.3,0.1

Type RM Length L Ch R = 1 ,1740.8  ,93.6,93.9,94.2
XS GIS Cut Line= 3
     1768862.612      245373.837     1768553.226      245417.885
     1768371.789      245264.765
#Sta/Elev= 30
       0 1416.14    19.8 1411.39     119 1390.85   133.9 1389.51   158.7 1388.78
   180.2 1385.42   188.5 1384.56   195.2 1386.14   203.4 1388.47   213.3 1389.85
   238.1 1388.94   257.9 1386.65   272.8 1386.52   297.6 1388.76   312.5 1391.47
   322.4 1391.17   337.2 1389.53     357 1392.34   371.9 1393.46   411.4 1394.56
   416.4 1396.76   436.2 1408.48     446 1412.88   460.9 1417.29   470.8 1422.18
   490.6 1435.64   510.4 1450.55   520.2 1456.63   535.1 1469.45   549.9 1481.23
#Mann= 3 , 0 , 0
       0      .1       0   180.2    .045       0   195.2      .1       0
#XS Ineff= 2 , 0
                          218.95         1395.04
Permanent Ineff=
       F       F
Bank Sta=180.2,195.2
XS Rating Curve= 0 ,0
Exp/Cntr=0.3,0.1

Type RM Length L Ch R = 1 ,1646.9  ,81.3,91.1,100.9
XS GIS Cut Line= 3
     1768842.685      245284.692     1768570.006      245323.496
      1768430.52      245241.692
#Sta/Elev= 30
       0 1406.89    24.6 1405.93    73.8 1398.65    88.5 1396.89   152.5  1382.8
   167.5 1382.14   177.1 1381.94   186.9 1382.33   206.6  1384.3   226.2 1385.22
   250.8 1390.41   255.8 1390.82   260.7 1390.13   270.5 1387.65   280.3 1386.77
     295 1388.09   309.7 1388.07   334.2  1386.7   348.9 1387.07   353.8 1387.67
   368.5 1392.12   373.4 1393.98   378.3 1396.81   388.1 1403.95   397.9 1412.05
   402.8 1415.37   412.6 1421.02   422.4 1424.41   427.3 1428.13   437.1 1438.38
#Mann= 3 , 0 , 0
       0      .1       0   152.5    .045       0   167.5      .1       0
Bank Sta=152.5,167.5
XS Rating Curve= 0 ,0
Exp/Cntr=0.3,0.1

Type RM Length L Ch R = 1 ,1555.9  ,92.3,91.3,90.3
XS GIS Cut Line= 2
      1768804.93      245249.034     1768451.495      245146.254
#Sta/Elev= 30
       0  1400.6    19.9 1398.91    29.8 1396.87    39.8 1393.23    59.7 1384.86
    64.7 1383.65    79.6 1383.97    89.5 1385.13    94.5 1384.87   108.1 1379.83
   114.4 1378.07   119.4 1378.06   123.1 1378.63   144.2 1382.48   149.2 1382.77
   179.1 1378.33   213.9 1378.84   233.8  1380.7   248.7 1383.71   263.6 1389.73
   288.5 1397.75   293.5 1400.27   303.4 1408.45   313.4 1417.97   318.3 1421.49
   328.3 1424.73   338.2 1427.14   343.2 1429.57   348.2 1433.49   368.1 1451.31
#Mann= 3 , 0 , 0
       0      .1       0   108.1    .045       0   123.1      .1       0
#XS Ineff= 2 , 0
                          149.16         1385.91
Permanent Ineff=
       F       F
Bank Sta=108.1,123.1
XS Rating Curve= 0 ,0
Exp/Cntr=0.3,0.1

Type RM Length L Ch R = 1 ,1464.6  ,178.6,191.7,204.9
XS GIS Cut Line= 3
     1769097.695       245305.35     1768797.838      245148.696
     1768227.823      245008.968
#Sta/Elev= 30
       0 1436.88   129.4 1418.88   228.9 1409.01   258.7  1403.3   293.5 1398.77
     403    1376     411 1375.45     426 1375.93   447.7 1378.31   487.5 1374.32
   497.5 1375.66   557.2 1392.16   562.1 1394.51     582 1408.88   601.9 1420.31
   616.8 1427.05   621.8 1428.42   646.7 1429.66   671.6 1438.64   691.4 1448.78
   721.3 1461.36   751.1 1483.65   761.1 1489.73     776 1496.16   790.9 1504.27
   805.8    1509   855.6 1534.69   875.5 1547.34   910.3 1561.21   925.2 1569.99
#Mann= 3 , 0 , 0
       0      .1       0     411    .045       0     426      .1       0
#XS Ineff= 2 , 0
                          444.98         1380.44
Permanent Ineff=
       F       F
Bank Sta=411,426
XS Rating Curve= 0 ,0
Exp/Cntr=0.3,0.1

Type RM Length L Ch R = 1 ,1272.8  ,617.7,600.3,585.6
XS GIS Cut Line= 3
     1768947.547      245124.605      1768716.96      244876.811
     1768494.978      244773.563
#Sta/Elev= 30
       0 1403.89    89.6 1390.21   119.5 1383.96   144.4 1381.62   169.2 1377.07
   194.1 1374.17     219 1370.12   229.1 1369.36     234  1368.8   244.1 1369.46
   253.9 1371.15   263.8 1371.46   288.7 1366.98   318.6 1366.33   363.5 1368.81
   393.4 1367.27   403.4 1369.14   408.4 1371.18   428.4 1383.22   448.4 1399.73
   463.4 1414.13   468.4 1418.14   473.4 1420.79   488.4 1421.86   513.4 1428.02
   528.3 1434.32   538.3 1439.84   543.3 1443.79   563.3 1465.28   583.3  1485.1
#Mann= 3 , 0 , 0
       0      .1       0   229.1    .045       0   244.1      .1       0
#XS Ineff= 2 , 0
                          260.94         1371.82
Permanent Ineff=
       F       F
Bank Sta=229.1,244.1
XS Rating Curve= 0 ,0
Exp/Cntr=0.3,0.1

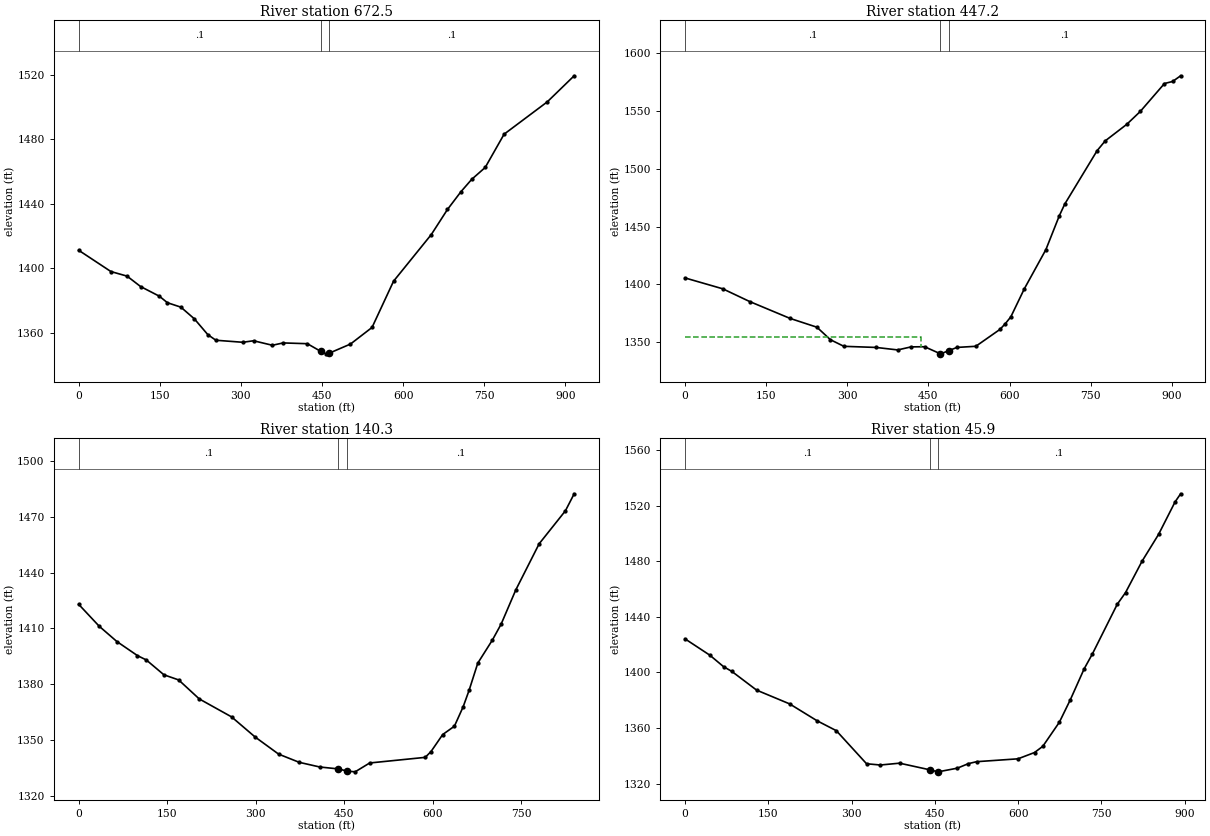
Type RM Length L Ch R = 1 ,672.5   ,215.7,225.3,233.1
XS GIS Cut Line= 3
     1769343.162      244448.383     1768881.126      244421.601
     1768437.996      244324.606
#Sta/Elev= 30
       0 1411.16    59.7 1397.96    89.6 1395.12   114.5 1388.69   149.3 1382.68
   164.2 1378.65   189.1  1375.9     214 1368.66   238.9 1358.88   253.8  1355.4
   303.6 1354.14   323.5 1355.08   358.3 1352.29   378.2 1353.74     423 1353.26
   447.9 1348.48   447.9 1348.47   457.8 1346.98   462.9 1347.32   502.7 1353.04
   542.6 1363.33   582.4 1391.99   652.2 1420.89   682.1 1436.43   707.1 1447.46
     727 1455.11   751.9 1462.45   786.8 1483.05   866.6 1503.06   916.4 1519.24
#Mann= 3 , 0 , 0
       0      .1       0   447.9    .045       0   462.9      .1       0
Bank Sta=447.9,462.9
XS Rating Curve= 0 ,0
Exp/Cntr=0.3,0.1

Type RM Length L Ch R = 1 ,447.2   ,304.6,306.9,306.2
XS GIS Cut Line= 3
     1769394.214      244388.155     1768963.467      244218.887
     1768572.542      243988.779
#Sta/Elev= 30
       0  1405.6    69.7 1396.19   119.4 1385.18   194.1 1370.57   243.8 1362.94
   268.7 1352.13   293.6 1346.39   353.3 1345.42   393.1 1343.27     418 1345.91
   442.9 1346.03   472.2  1339.9   472.8 1339.88   487.2 1342.59   502.7 1345.44
   537.6 1346.41   582.4 1361.09   592.4 1366.14   602.4 1371.94   627.3 1396.18
   667.2 1430.13   692.1 1459.54   702.1 1469.59   761.9 1515.81   776.9 1524.31
   816.7 1538.62   841.7 1549.76   886.5 1573.99   901.5 1575.75   916.4 1580.69
#Mann= 3 , 0 , 0
       0      .1       0   472.2    .045       0   487.2      .1       0
#XS Ineff= 2 , 0
          435.78 1354.22
Permanent Ineff=
       F       F
Bank Sta=472.2,487.2
XS Rating Curve= 0 ,0
Exp/Cntr=0.3,0.1

Type RM Length L Ch R = 1 ,140.3   ,92.8,94.4,98.2
XS GIS Cut Line= 3
     1769487.875      244205.702     1769104.139      243945.862
     1768741.051      243847.777
#Sta/Elev= 30
       0 1422.98    34.9 1411.15    64.8 1402.94    99.7 1395.35   114.6 1393.03
   144.5 1385.03   169.4 1382.28   204.3 1372.07   259.1 1362.39     299 1351.56
   338.8 1342.35   373.7 1337.94   408.6 1335.42   439.9  1334.4   454.9 1333.23
   468.4 1332.82   493.1 1337.59   587.2 1340.61     597 1343.75   616.8  1352.9
   636.6 1357.37   651.5 1367.88   661.4 1376.61   676.2 1391.31     701 1403.76
   715.8 1412.33   740.6 1430.71   780.2 1455.55   824.7  1473.3   839.5 1482.44
#Mann= 3 , 0 , 0
       0      .1       0   439.9    .045       0   454.9      .1       0
Bank Sta=439.9,454.9
XS Rating Curve= 0 ,0
Exp/Cntr=0.3,0.1

Type RM Length L Ch R = 1 ,45.9    ,43.3,45.9,48.4
XS GIS Cut Line= 3
     1769517.129      244150.636     1769147.159      243859.823
     1768730.727      243790.991
#Sta/Elev= 30
       0  1424.2    44.6 1412.46    69.4 1404.16    84.2 1400.79   128.8  1387.3
   188.2  1377.4   237.8 1365.21   272.4 1358.08   326.9 1334.24   351.7 1333.34
   386.4 1334.66   440.5 1329.91   455.5 1328.43   455.7 1328.42   490.4 1331.06
   510.3 1334.33   525.2 1335.74   599.7  1337.8   629.5 1342.34   644.4 1346.82
   674.2 1364.16     694 1380.38   718.9 1402.65   733.8 1413.43   778.5 1449.16
   793.4 1457.55   823.2 1480.19   852.9 1499.48   882.7 1522.94   892.7 1528.77
#Mann= 3 , 0 , 0
       0      .1       0   440.5    .045       0   455.5      .1       0
Bank Sta=440.5,455.5
XS Rating Curve= 0 ,0
Exp/Cntr=0.3,0.1

Chan Stop Cuts=-1
Use User Specified Reach Order=0